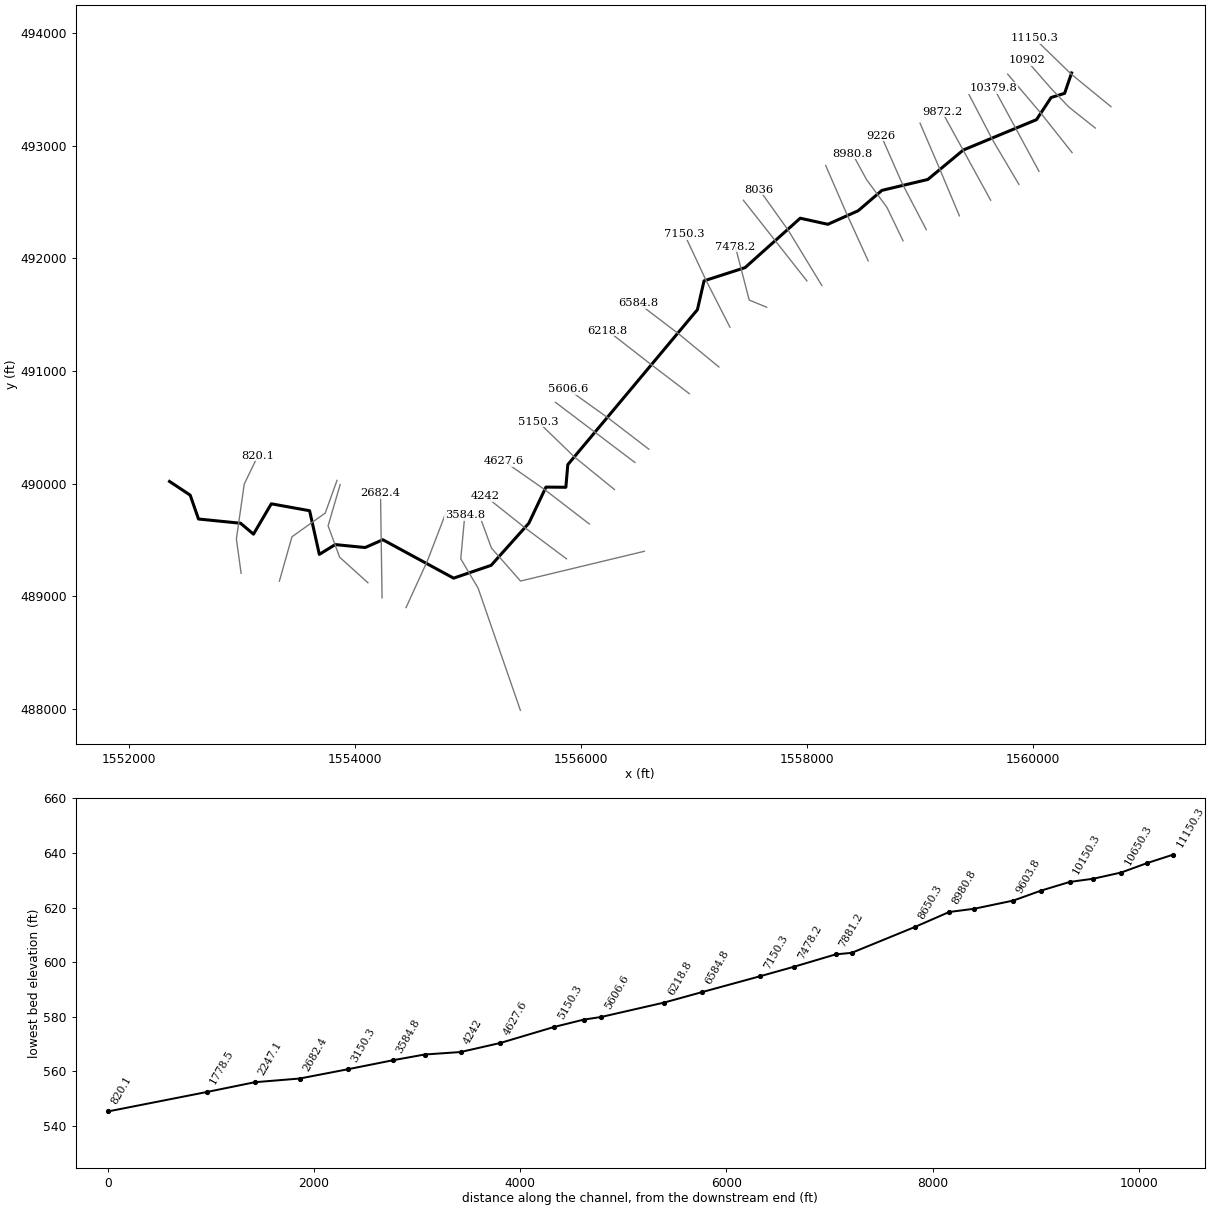
--- RFCAMPCR.prj (project) ---

Proj Title=RFCAMPCR
Current Plan=p01
Default Exp/Contr=0,0
English Units
Geom File=g01
Flow File=f01
Plan File=p01
BEGIN DESCRIPTION:
END DESCRIPTION:
DSS Export Rating Curves= 0
DSS Export Rating Curve Sorted= 0
DSS Export Volume Flow Curves= 0
DXF OffsetX= 0
DXF OffsetY= 0
DXF ScaleX= 0
DXF ScaleY= 0

--- RFCAMPCR.p01 (plan) ---

Plan Title=Floodplain
Program Version=4.00
Geom File=g01
Flow File=f01
K Sum by GR=0
Std Step Tol=0.01
Critical Tol=0.01
Num of Std Step Trials=20
Max Error Tol=0.3
Flow Tol Ratio=0.001
Split Flow NTrial=30
Split Flow Tol=0.02
Split Flow Ratio=0.02
Log Output Level=0
Friction Slope Method=1
Unsteady Friction Slope Method=2
Unsteady Bridges Friction Slope Method=1
Global Log Level=0
CheckData=False
Run HTab=0
Run UNet=0
Run PostProcess=0
UNET Theta=0
UNET Theta Warmup=0
UNET ZTol=0
UNET ZSATol=0
UNET MxIter=0
UNET MaxInSteps=0
UNET DtIC=0
UNET DtMin=0
UNET MaxCRTS=0
UNET WFStab=0
UNET SFStab=0
UNET WFX=0
UNET SFX=0
UNET DSS MLevel=0
UNET DZMax Abort=0
UNET Convert EG Bridges=0
UNET Use Existing IB Tables=0
UNET Froude Limit=0
UNET Froude Power=0
Write IC File=0
Echo Input=False
Echo Output=False
Write Detailed=0

--- RFCAMPCR.f01 (steady flow) ---

Flow Title=NFF Regression Equation
Program Version=4.00
Number of Profiles=1
Profile Names=P100yr
River Rch & RM=RFCAMPCR,Main      ,11150.3
     379
River Rch & RM=RFCAMPCR,Main      ,9872.2
     392
River Rch & RM=RFCAMPCR,Main      ,8980.8
     435
River Rch & RM=RFCAMPCR,Main      ,7478.2
     469
River Rch & RM=RFCAMPCR,Main      ,6584.8
     517
River Rch & RM=RFCAMPCR,Main      ,3893.9
     559
River Rch & RM=RFCAMPCR,Main      ,3584.8
     852
Boundary for River Rch & Prof#=RFCAMPCR,Main      ,1
Up Type=0
Dn Type=3
Dn Slope=0.006077

--- RFCAMPCR.g01 (geometry) ---

Geom Title=USGS 10m DEM
Program Version=4.00

River Reach=RFCAMPCR        ,Main
Reach XY= 30
     1560339.826       493645.45     1560277.956      493464.582
     1560158.771      493427.522     1560029.248      493230.965
     1559382.587      492961.774     1559067.944      492700.059
     1558661.736      492603.078     1558451.903      492422.359
     1558183.712      492302.071     1557939.754      492356.085
     1557451.704       491917.57     1557088.534      491800.165
     1557030.045      491544.278     1555883.502      490168.683
     1555866.295      489967.839     1555690.317      489969.411
     1555538.715       489648.73     1555205.421       489274.95
     1554873.326      489161.183     1554247.372      489502.208
     1554091.204      489432.843     1553826.211      489459.139
      1553685.78       489372.13     1553599.691      489759.701
     1553260.857       489821.04     1553103.293      489551.628
     1552988.867        489648.6     1552616.911      489686.043
     1552543.526      489897.949     1552360.682      490019.752

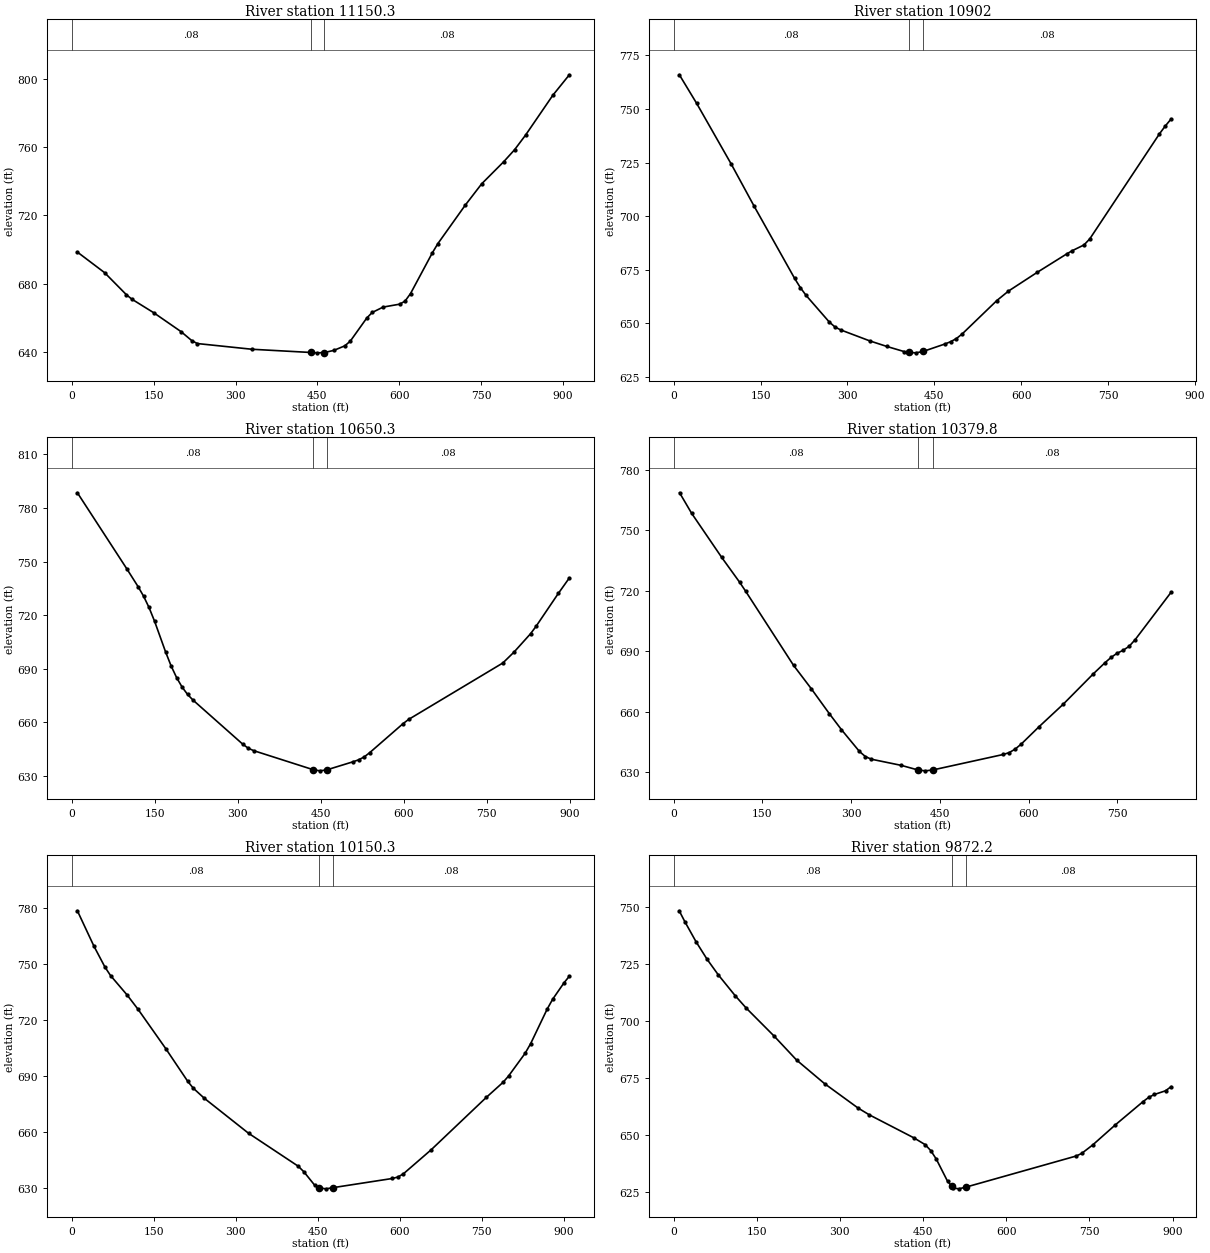
Type RM Length L Ch R = 1 ,11150.3 ,250.3,248.3,249.6
XS GIS Cut Line= 3
     1560688.134       493346.19     1560332.835        493638.3
     1560009.867      493954.088
#Sta/Elev= 30
      10  698.51      60   686.4     100  673.44     110  670.84     150  662.89
     200  651.82     220  646.46     230   644.8     330  641.45   437.5  639.57
     450  639.35   462.5   639.5     480  640.78   500.1  643.44   510.2  646.19
   540.3  659.71   550.3  663.03   570.4   666.2   600.5   667.9   610.5  669.67
   620.6  674.11   660.7  698.08   670.8  703.47   720.9     726   751.1  738.56
   791.2  751.43   811.3  758.53   831.4  767.11   881.5  790.54   911.7  802.52
#Mann= 3 , 0 , 0
       0     .08       0   437.5    .045       0   462.5     .08       0
Bank Sta=437.5,462.5
XS Rating Curve= 0 ,0
Exp/Cntr=0.3,0.1

Type RM Length L Ch R = 1 ,10902   ,253,251.7,248.8
XS GIS Cut Line= 4
     1560549.693      493156.328     1560316.321      493342.235
     1560158.102      493508.364     1559940.552      493757.558
#Sta/Elev= 30
     9.9  765.89    39.8  752.56    99.5  724.26   139.2  704.54   208.9  670.98
   218.8  666.68   228.7  663.06   268.5  650.73   278.5  648.37   288.4     647
   338.3  641.91   368.2  639.28   398.1  636.89   405.6  636.52   418.1  636.32
   430.6  636.97   467.9  640.41   477.9  641.49   487.9  642.95   497.9  645.09
   557.9   660.7   577.9   665.1     628  673.91   678.1  682.36   688.2  683.95
   708.2  686.59   718.2  689.41   838.5  738.38   848.6  742.04   858.6   745.3
#Mann= 3 , 0 , 0
       0     .08       0   405.6    .045       0   430.6     .08       0
Bank Sta=405.6,430.6
XS Rating Curve= 0 ,0
Exp/Cntr=0.3,0.1

Type RM Length L Ch R = 1 ,10650.3 ,275.6,270.5,264.5
XS GIS Cut Line= 3
     1560344.009      492938.778     1560065.948      493290.688
     1559774.423      493634.938
#Sta/Elev= 30
      10  788.55    99.7  745.81   119.6  736.07   129.6  730.71   139.5  724.34
   149.5  716.68   169.4  699.52   179.4  691.66   189.4  685.06   199.3  679.77
   209.3  675.61   219.3   672.4     309  647.78   318.9  645.53   328.9  644.14
     436  633.53   448.5  632.85     461   633.4   508.7  637.95   518.7  639.04
   528.7  640.65   538.7  643.06   598.9  659.28   608.9  661.63   779.3  693.24
   799.4   699.3   829.4  709.61   839.5  713.82   879.6  732.17   899.6  740.88
#Mann= 3 , 0 , 0
       0     .08       0     436    .045       0     461     .08       0
Bank Sta=436,461
XS Rating Curve= 0 ,0
Exp/Cntr=0.3,0.1

Type RM Length L Ch R = 1 ,10379.8 ,228.4,229.5,229
XS GIS Cut Line= 2
     1560051.305      492772.649     1559651.804      493512.319
#Sta/Elev= 30
    10.1  768.54    30.4  758.38      81  736.59   111.4  724.22   121.5   719.8
   202.6  682.95     233  671.19   263.3  658.89   283.6  651.02     314   640.2
   324.1  637.66   334.2  636.35   384.9  633.28   412.9  631.01   425.4  630.58
   437.9  631.01   557.1   638.7   567.2  639.64   577.3  641.39   587.5  643.88
   617.8  652.55   658.4  663.64     709  678.64   729.2  684.29   739.4  686.89
   749.5  688.94   759.6  690.39   769.8  692.37   779.9  695.65   840.7  719.19
#Mann= 3 , 0 , 0
       0     .08       0   412.9    .045       0   437.9     .08       0
Bank Sta=412.9,437.9
XS Rating Curve= 0 ,0
Exp/Cntr=0.3,0.1

Type RM Length L Ch R = 1 ,10150.3 ,279,278.1,278.7
XS GIS Cut Line= 3
     1559873.476       492656.72     1559642.274      493048.422
     1559432.528      493453.177
#Sta/Elev= 30
    10.1  778.64    40.4  759.66    60.6  748.41    70.8  743.88   101.1  733.46
   121.3  725.71   171.8  704.69   212.3  687.02   222.4  683.37   242.6  677.97
   323.4  659.23   414.4  641.53   424.5  638.61   444.7  631.27   452.5  629.94
     465  629.39   477.5     630   586.5  634.94   596.7  635.71   606.8  637.43
   657.5  650.29   758.8  678.51   789.2  686.53   799.3  689.91   829.7  702.14
   839.8   707.3   870.2  725.94   880.3  731.23   900.6  739.85   910.7  743.55
#Mann= 3 , 0 , 0
       0     .08       0   452.5    .045       0   477.5     .08       0
Bank Sta=452.5,477.5
XS Rating Curve= 0 ,0
Exp/Cntr=0.3,0.1

Type RM Length L Ch R = 1 ,9872.2  ,271.3,268.4,265.6
XS GIS Cut Line= 2
     1559624.116      492515.544     1559192.971       493302.68
#Sta/Elev= 30
    10.1  748.47    20.2  743.71    40.3  734.93    60.5  727.11    80.7  720.27
   110.9  711.19   131.1  705.66   181.5  693.33   221.8  682.85   272.3  672.47
   332.8  661.73   352.9  658.77   433.6  648.61   453.8  645.64   463.9  643.03
   473.9  639.28   494.1  629.59   501.8  627.35   504.2  626.65   514.3  626.21
   526.8  626.93   726.1  640.63   736.1  641.77   756.3  645.56   796.6  654.28
   847.1  664.61   857.1  666.42   867.2  667.69   887.4  669.32   897.5  671.15
#Mann= 3 , 0 , 0
       0     .08       0   501.8    .045       0   526.8     .08       0
Bank Sta=501.8,526.8
XS Rating Curve= 0 ,0
Exp/Cntr=0.3,0.1

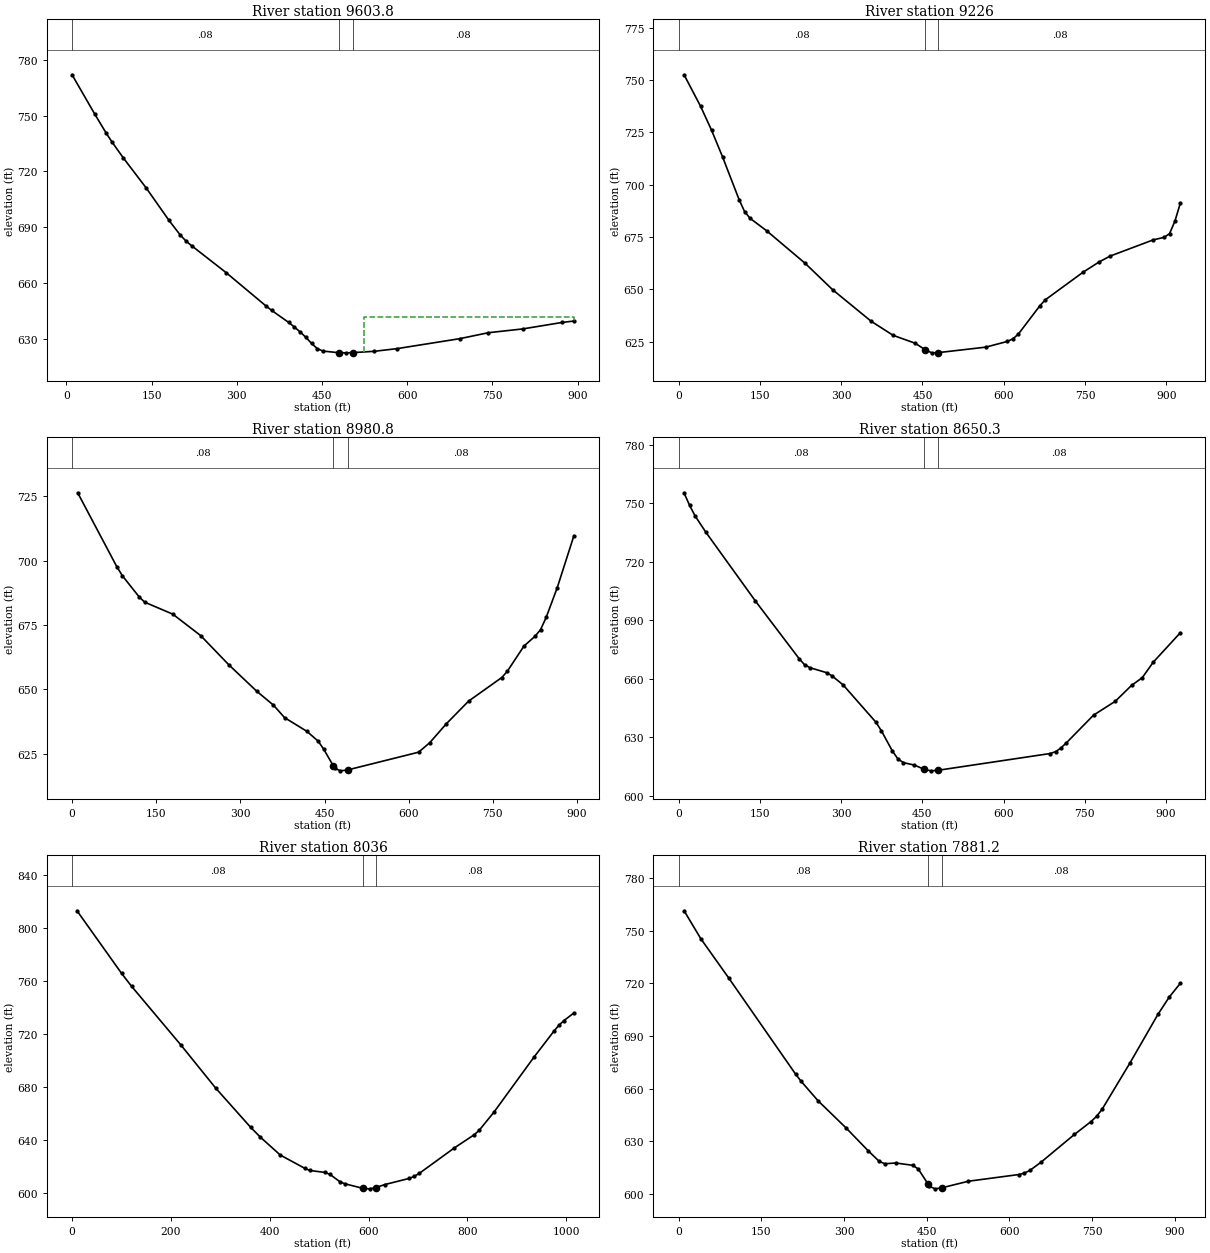
Type RM Length L Ch R = 1 ,9603.8  ,375.7,377.8,378
XS GIS Cut Line= 3
     1559347.234      492377.103     1559165.283      492812.203
     1558999.154      493199.838
#Sta/Elev= 30
      10  771.87    50.2  750.62    70.2  740.48    80.3  735.77   100.3   727.2
   140.5  711.09   180.6   693.7   200.7  685.72   210.7  682.56   220.8     680
     281  665.68   351.2  647.78   361.2  645.38   391.3   638.9   401.4  636.41
   411.4  633.82   421.4  630.94   431.5  627.65   441.5  624.88   451.5  623.52
   479.2  622.65   491.7  622.57   504.2  622.68   541.9  623.39   582.1  624.83
   692.5  630.18   742.7  633.37     803   635.4   873.3  638.92   893.3  639.64
#Mann= 3 , 0 , 0
      10     .08       0   479.2    .045       0   504.2     .08       0
#XS Ineff= 2 , 0
                          523.22          641.86
Permanent Ineff=
       F       F
Bank Sta=479.2,504.2
XS Rating Curve= 0 ,0
Exp/Cntr=0.3,0.1

Type RM Length L Ch R = 1 ,9226    ,240.9,245.1,251.2
XS GIS Cut Line= 3
      1559054.53      492254.484     1558839.054      492668.879
     1558655.029      493089.085
#Sta/Elev= 30
    10.2   752.5    40.6  737.48    60.9  726.02    81.2  713.27   111.7  692.84
   121.8  687.13     132  683.88   162.5  677.94   233.5   662.4   284.3  649.75
   355.4  634.67     396  627.94   436.6  624.17   454.6  621.14   467.1  619.58
   479.6   619.7   566.8   622.3   606.7  625.03   616.7  626.25   626.6  628.42
   666.5  642.03   676.5  644.89   746.3  658.11   776.2  663.06   796.2  665.82
   875.9  673.59   895.9  674.79   905.9  676.56   915.8  682.51   925.8  691.12
#Mann= 3 , 0 , 0
       0     .08       0   454.6    .045       0   479.6     .08       0
Bank Sta=454.6,479.6
XS Rating Curve= 0 ,0
Exp/Cntr=0.3,0.1

Type RM Length L Ch R = 1 ,8980.8  ,336.3,330.5,324.3
XS GIS Cut Line= 4
     1558848.846      492155.597      1558706.45      492452.257
     1558524.499      492701.451      1558401.88      492926.912
#Sta/Elev= 30
      10  726.37    79.8  697.63    89.7  694.14   119.7  685.89   129.6  683.86
   179.5  679.23   229.3  670.88   279.2  659.59   329.1  649.29   358.9  643.89
   378.8  639.02   418.6   633.7   438.6   629.9   448.5  626.78   465.9  620.19
   468.4  619.34   478.4  618.37   490.9  618.71   617.7  625.62   637.6  629.33
   667.2  636.69   706.7  645.45   765.9  654.62   775.8  657.07   805.4  666.83
   825.2  670.66     835  673.23   844.9  677.93   864.7  689.52   894.3  709.64
#Mann= 3 , 0 , 0
       0     .08       0   465.9    .045       0   490.9     .08       0
Bank Sta=465.9,490.9
XS Rating Curve= 0 ,0
Exp/Cntr=0.3,0.1

Type RM Length L Ch R = 1 ,8650.3  ,608.8,614.3,620.1
XS GIS Cut Line= 3
     1558540.321      491977.602     1558347.629      492401.638
     1558164.552       492824.07
#Sta/Elev= 30
    10.1  755.32    20.3  748.94    30.4  743.54    50.6  735.05   141.8  699.92
   222.8  670.29   232.9  667.19     243   665.7   273.4  663.18   283.5  661.51
   303.8  656.92   364.5  637.77   374.6  633.32   394.9  622.98     405     619
   415.1  617.11   435.4  615.86   453.3  613.69   465.8  612.91   478.3  613.17
     686  621.78     696  622.74     706  624.64     716  627.29     766  641.42
   806.1  648.53   836.1  656.64   856.1  660.67   876.1  668.52   926.2  683.64
#Mann= 3 , 0 , 0
       0     .08       0   453.3    .045       0   478.3     .08       0
Bank Sta=453.3,478.3
XS Rating Curve= 0 ,0
Exp/Cntr=0.3,0.1

Type RM Length L Ch R = 1 ,8036    ,153.7,154.8,155.8
XS GIS Cut Line= 3
     1558130.414      491759.071     1557834.021      492248.101
     1557576.728      492609.704
#Sta/Elev= 30
      10  813.08   100.3  765.82   120.4  756.15   220.7  711.67   290.9  679.27
   361.2   649.9   381.2  642.35   421.4  628.89   471.5  618.79   481.5  617.24
   511.6  615.81   521.7  614.39   541.7  608.86   551.8  607.25   589.6  603.69
   602.1  603.41   614.6  604.32   632.4  606.58   682.8  611.31   692.9  612.88
     703  615.14   773.6  634.23   813.9  644.19     824  647.54   854.3  661.46
   934.9  702.73   975.3  722.33   985.4  726.76   995.5  730.27  1015.6     736
#Mann= 3 , 0 , 0
       0     .08       0   589.6    .045       0   614.6     .08       0
Bank Sta=589.6,614.6
XS Rating Curve= 0 ,0
Exp/Cntr=0.3,0.1

Type RM Length L Ch R = 1 ,7881.2  ,414.3,403,391.7
XS GIS Cut Line= 2
     1557998.423      491799.606     1557436.748      492515.544
#Sta/Elev= 30
    10.1  761.33    40.4   745.4      91  723.03   212.3  668.22   222.4  664.12
   252.8  653.11   303.3  637.73   343.8  624.59     364  618.49   374.1  617.15
   394.3  617.58   424.7  616.25   434.8  614.16   452.6  605.53     455  604.35
   465.1  602.85   477.6  603.45   525.8  607.19   616.8  610.99   626.9  611.76
     637  613.31   657.2  617.99   717.9  633.84   748.2  641.22   758.3  644.22
   768.4  648.32     819  674.77   869.5  702.33   889.7  712.06     910     720
#Mann= 3 , 0 , 0
       0     .08       0   452.6    .045       0   477.6     .08       0
Bank Sta=452.6,477.6
XS Rating Curve= 0 ,0
Exp/Cntr=0.3,0.1

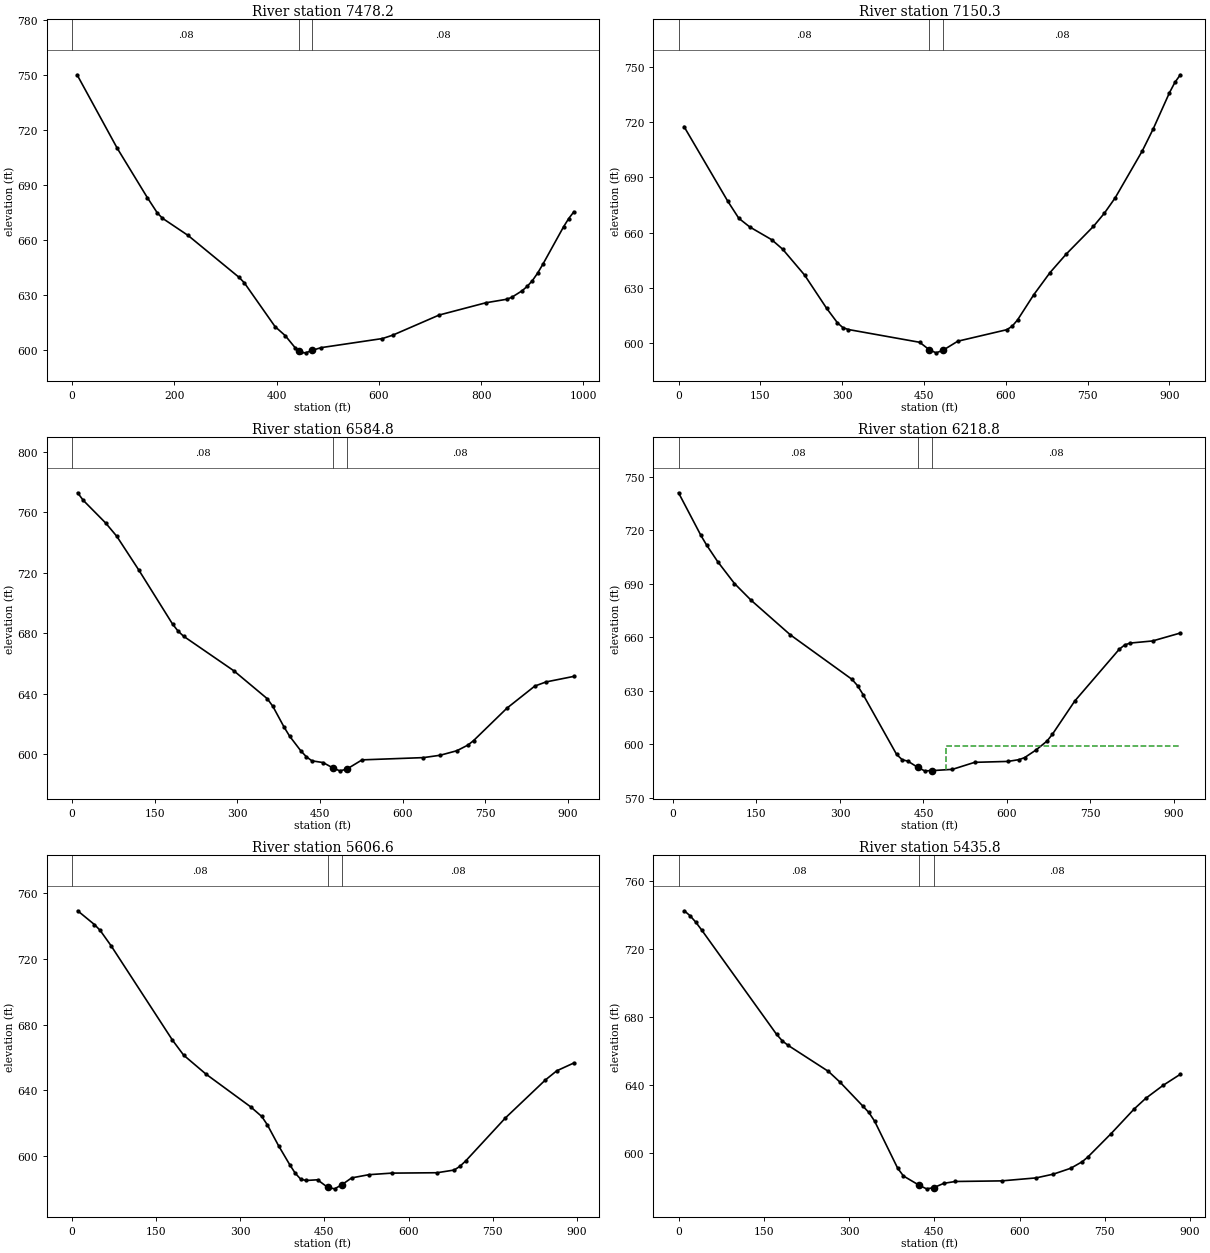
Type RM Length L Ch R = 1 ,7478.2  ,321.9,327.9,333.1
XS GIS Cut Line= 3
     1557642.432      491566.234     1557488.169      491629.522
      1557365.55      492104.177
#Sta/Elev= 30
     9.8  750.01    88.3  709.94   147.1  683.05   166.7  674.65   176.7  671.76
   226.8  662.38   326.8  639.46   336.8  636.55   396.9  612.66   416.9  607.71
   436.9  600.89   444.4  599.11   446.9  598.52   456.9  598.33   469.4  599.67
   486.9  601.16     607  606.13     627  607.96   717.8  618.95     809  625.63
   849.6  627.54   859.7   628.6     880  632.17   890.1  634.61   900.2  637.73
   910.4   641.8   920.5  646.56   961.1  667.05   971.2  671.58   981.3  675.26
#Mann= 3 , 0 , 0
       0     .08       0   444.4    .045       0   469.4     .08       0
Bank Sta=444.4,469.4
XS Rating Curve= 0 ,0
Exp/Cntr=0.3,0.1

Type RM Length L Ch R = 1 ,7150.3  ,553.2,565.6,578.8
XS GIS Cut Line= 3
     1557318.085      491388.239     1557104.157      491809.207
     1556914.628      492214.929
#Sta/Elev= 30
      10  717.61    90.4  677.03   110.5  667.84   130.6  663.13   170.8  656.22
   190.9  651.07   231.1  637.05   271.3  619.11   291.4  611.13   301.4  608.51
   311.5   607.5   442.1  600.58   459.7  596.54   472.2  594.86   484.7  596.23
     512  601.17   601.6  607.39   611.5  609.24   621.5  612.69   651.3  626.38
   681.2  638.43     711  648.49   760.8  663.48   780.7  670.57   800.6  678.95
   850.4  704.45   870.3  716.33   900.1  735.96   910.1  741.57     920  745.67
#Mann= 3 , 0 , 0
       0     .08       0   459.7    .045       0   484.7     .08       0
Bank Sta=459.7,484.7
XS Rating Curve= 0 ,0
Exp/Cntr=0.3,0.1

Type RM Length L Ch R = 1 ,6584.8  ,366,366,365.7
XS GIS Cut Line= 3
     1557220.189      491035.605     1556869.065      491325.578
      1556507.77      491602.037
#Sta/Elev= 30
    10.1  772.96    20.2     768    60.7  753.06      81  744.23   121.4  721.66
   182.2  686.16   192.3  681.45   202.4  678.04   293.5   655.2   354.2  636.71
   364.3  631.66   384.5  618.02   394.7  611.94   414.9  602.29     425  598.33
   435.1  595.64   455.4  594.49   473.2  590.94   485.7  589.02   498.2  590.11
   526.1  596.28   637.4  597.77   667.7  599.33     698  602.31   718.2  606.08
   728.3     609     789  630.52   839.5  645.11   859.8  647.83   910.3  651.51
#Mann= 3 , 0 , 0
       0     .08       0   473.2    .045       0   498.2     .08       0
Bank Sta=473.2,498.2
XS Rating Curve= 0 ,0
Exp/Cntr=0.3,0.1

Type RM Length L Ch R = 1 ,6218.8  ,611.7,612.2,613.3
XS GIS Cut Line= 3
     1556958.138      490798.876     1556599.318      491073.815
     1556237.256      491356.595
#Sta/Elev= 30
      10  740.91    50.2  717.02    60.3   711.7    80.4  702.32   110.5  690.09
   140.6  680.66     211  661.31   321.5  636.46   331.5  632.93   341.5  627.92
   401.8  594.36   411.9   591.4   421.9  590.64   439.5  587.19     452   585.2
   464.5   585.3     502  586.03   541.9  589.96   601.8  590.48   621.8  591.48
   631.8  592.63   651.8  596.79   671.8  601.83   681.7  605.72   721.7  624.27
   801.6  653.26   811.6  655.74   821.6  656.76   861.5  657.93   911.4  662.37
#Mann= 3 , 0 , 0
      10     .08       0   439.5    .045       0   464.5     .08       0
#XS Ineff= 2 , 0
                          489.85          599.06
Permanent Ineff=
       F       F
Bank Sta=439.5,464.5
XS Rating Curve= 0 ,0
Exp/Cntr=0.3,0.1

Type RM Length L Ch R = 1 ,5606.6  ,171.2,170.8,170
XS GIS Cut Line= 3
     1556600.106      490306.043     1556245.301       490579.18
      1555882.19      490840.029
#Sta/Elev= 30
      10  749.44    39.8  741.07    49.8  737.61    69.7  728.06   179.1  670.54
     199  661.41   238.8  649.86   318.4  629.92   338.3  624.02   348.3  618.91
   368.2  606.23   388.1  594.67     398  589.43     408   585.7   417.9  585.01
   437.8  585.42   455.6  580.87   468.1   579.9   480.6  582.28   498.6  586.57
   529.1  588.52   569.7  589.48     651  589.72   681.5  591.37   691.6  593.62
   701.8  596.84   772.9  623.16     844  646.25   864.4  651.87   894.9  656.64
#Mann= 3 , 0 , 0
       0     .08       0   455.6    .045       0   480.6     .08       0
Bank Sta=455.6,480.6
XS Rating Curve= 0 ,0
Exp/Cntr=0.3,0.1

Type RM Length L Ch R = 1 ,5435.8  ,286.4,285.5,282.1
XS GIS Cut Line= 2
      1556477.55      490187.758     1555774.467      490721.744
#Sta/Elev= 30
    10.1  742.52    20.3   739.6    30.4   735.8    40.6  731.26   172.5  669.82
   182.7  665.95   192.8  663.34   263.8     648   284.1   641.7   324.7  627.47
   334.9  623.84     345  618.74   385.6  591.03   395.8  586.46   423.9  580.93
   436.4  578.92   448.9   579.6   466.8  582.17   487.1  583.25   568.3   583.6
   629.2  585.36   659.6  587.58   690.1  591.03   710.4   594.9   720.5  597.75
   761.1  611.41   801.7  625.91     822  632.16   852.4  639.76   882.9  646.33
#Mann= 3 , 0 , 0
       0     .08       0   423.9    .045       0   448.9     .08       0
Bank Sta=423.9,448.9
XS Rating Curve= 0 ,0
Exp/Cntr=0.3,0.1

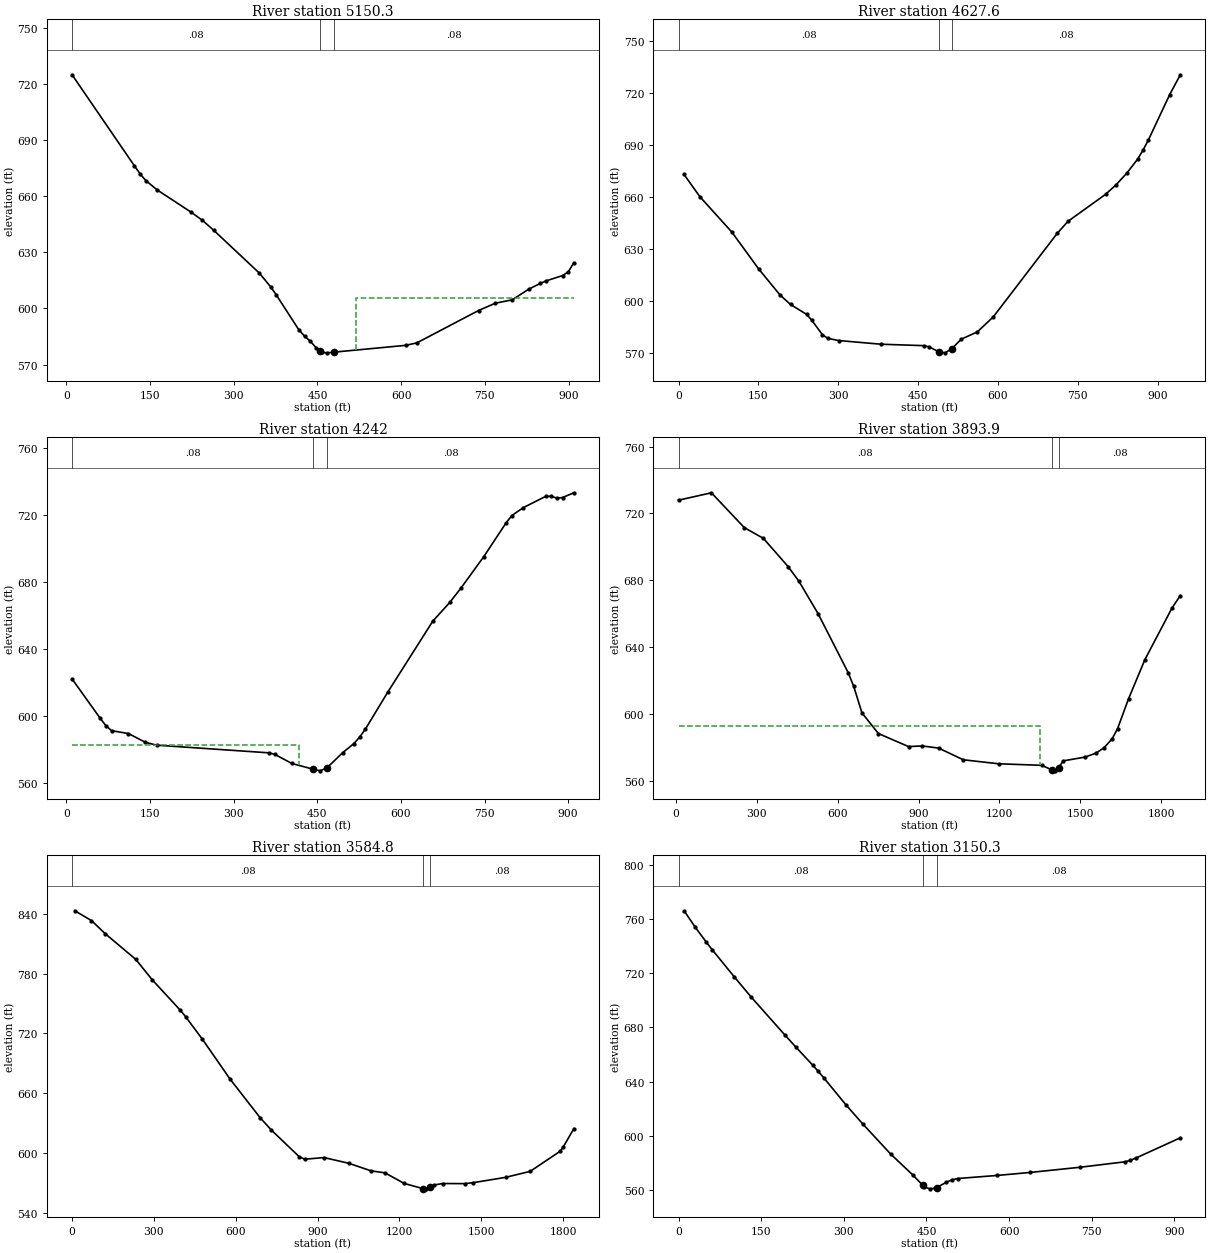
Type RM Length L Ch R = 1 ,5150.3  ,521.9,522.7,528.1
XS GIS Cut Line= 3
     1556296.588      489947.464     1555942.384      490236.697
     1555618.017      490551.639
#Sta/Elev= 30
    10.2  724.76   121.9  676.14   132.1  671.85   142.3  668.27   162.6  663.29
   223.6  651.36   243.9     647   264.2  641.66   345.5  618.92   365.8   611.6
     376  607.26   416.6  588.53   426.8  585.17     437   582.5   447.1   579.1
   454.8  577.16   457.3  576.53   467.3  576.25   479.8  576.63     608  580.25
   628.1  581.58   738.6  598.86   768.7  602.76   798.9  604.56     829  610.34
   849.1   613.3   859.2  614.64   889.3  617.53   899.4   619.5   909.4   624.4
#Mann= 3 , 0 , 0
    10.2     .08       0   454.8    .045       0   479.8     .08       0
#XS Ineff= 2 , 0
                          518.95          605.63
Permanent Ineff=
       F       F
Bank Sta=454.8,479.8
XS Rating Curve= 0 ,0
Exp/Cntr=0.3,0.1

Type RM Length L Ch R = 1 ,4627.6  ,384,385.7,384
XS GIS Cut Line= 3
     1556074.093      489641.905     1555677.721      489947.933
     1555315.874      490201.385
#Sta/Elev= 30
      10  673.25    40.1  660.31   100.2  639.89   150.2  618.83   190.3   603.8
   210.3  598.22   240.4  592.57   250.4   589.1   270.4  580.76   280.4  578.73
   300.5  577.46   380.6  575.33   460.7  574.51   470.7  573.81   488.3  571.03
   500.8  570.37   513.3  572.73   530.9  578.22     561  582.39   591.1  591.05
   711.6  639.32   731.7  646.16     802  661.65   822.1  667.25   842.1   673.9
   862.2  681.92   872.3  687.05   882.3  692.84   922.5  719.08   942.5  730.53
#Mann= 3 , 0 , 0
       0     .08       0   488.3    .045       0   513.3     .08       0
Bank Sta=488.3,513.3
XS Rating Curve= 0 ,0
Exp/Cntr=0.3,0.1

Type RM Length L Ch R = 1 ,4242    ,353.8,348.1,343.3
XS GIS Cut Line= 3
     1555872.188      489332.697     1555508.239      489605.692
     1555152.434       489889.69
#Sta/Elev= 30
    10.1  622.02    60.7  598.41    70.8  594.06    80.9  591.08   111.2  589.35
   141.5  584.12   161.8   582.4     364   577.8   374.1  576.84   404.4  571.45
   442.5  568.03     455  567.05   467.5   568.9   495.4  577.87   515.7  583.37
   525.8  587.19   535.9  591.82   576.4  614.13   657.3  656.63   687.6  667.75
   707.9  676.45   748.3     695   788.8  715.41   798.9  719.71   819.2   724.4
   859.6  731.19   869.7  731.27   879.9  730.09     890  730.51   910.2  733.34
#Mann= 3 , 0 , 0
    10.1     .08       0   442.5    .045       0   467.5     .08       0
#XS Ineff= 2 , 0
          416.85  582.31
Permanent Ineff=
       F       F
Bank Sta=442.5,467.5
XS Rating Curve= 0 ,0
Exp/Cntr=0.3,0.1

Type RM Length L Ch R = 1 ,3893.9  ,314.3,309.1,303.9
XS GIS Cut Line= 4
     1556560.707      489399.617     1555465.355      489135.453
     1555208.048      489428.419     1555086.218      489760.568
#Sta/Elev= 30
    10.2  727.92     132  732.35   253.8  711.55   324.8   705.1   416.2  688.27
   456.8  679.43   527.8  660.01   639.5  624.73   659.8  616.57   690.3  600.75
   751.2  588.44   862.8  580.64   913.6  581.02   974.5  579.73  1065.9  572.75
  1196.7  570.36  1356.7  569.44  1394.2  566.72  1406.7  566.14  1419.2  568.05
  1436.7  572.11  1516.7  574.35  1557.1  576.66  1587.4  579.92  1617.8  585.28
    1638  591.44  1678.4  609.16  1739.1   632.6  1840.1  663.61  1870.5  670.89
#Mann= 3 , 0 , 0
    10.2     .08       0  1394.2    .045       0  1419.2     .08       0
#XS Ineff= 2 , 0
         1350.42  592.65
Permanent Ineff=
       F       F
Bank Sta=1394.2,1419.2
XS Rating Curve= 0 ,0
Exp/Cntr=0.3,0.1

Type RM Length L Ch R = 1 ,3584.8  ,461.1,434.5,409.6
XS GIS Cut Line= 4
     1555464.062      487988.309     1555090.246      489072.422
     1554936.797      489332.546     1554972.501      489721.268
#Sta/Elev= 30
    10.1  843.19      71  833.37   121.8  820.11   233.4  794.41   294.3  773.75
   395.8  743.62   416.1  736.88     477  714.49   578.4  674.45   690.1  635.16
   730.7  622.93   832.2  596.37   852.5  593.76   923.5  595.43  1014.8  589.64
    1096  582.07  1146.8  580.09  1217.2  569.46  1285.3  564.29  1297.8  564.03
  1310.3  565.54    1328  567.96  1358.2  569.37  1438.7  569.26  1468.8  570.17
  1588.9  575.55    1679  581.58  1789.1  601.78  1799.1  605.56  1839.1  624.47
#Mann= 3 , 0 , 0
       0     .08       0  1285.3    .045       0  1310.3     .08       0
Bank Sta=1285.3,1310.3
XS Rating Curve= 0 ,0
Exp/Cntr=0.3,0.1

Type RM Length L Ch R = 1 ,3150.3  ,455,467.9,479.2
XS GIS Cut Line= 3
     1554452.707      488899.889     1554641.636      489314.935
     1554804.556      489739.574
#Sta/Elev= 30
    10.1  766.16    30.4  753.98    50.7  742.81    60.8  737.55   101.3  717.31
   131.7   702.5   192.5  674.64   212.8  665.53   243.2  652.29   253.3  647.66
   263.5  642.83     304  622.75   334.4  608.69   385.1  586.44   425.6  570.84
   443.5  563.31   445.9  562.34     456  560.75   466.1   561.2   468.5   561.7
   486.3  565.64   496.5  567.41   506.6  568.37   577.3  570.61     638  572.85
   728.9   576.7   809.8  580.69   819.9   581.8     830  583.46   910.8  598.45
#Mann= 3 , 0 , 0
       0     .08       0   443.5    .045       0   468.5     .08       0
Bank Sta=443.5,468.5
XS Rating Curve= 0 ,0
Exp/Cntr=0.3,0.1

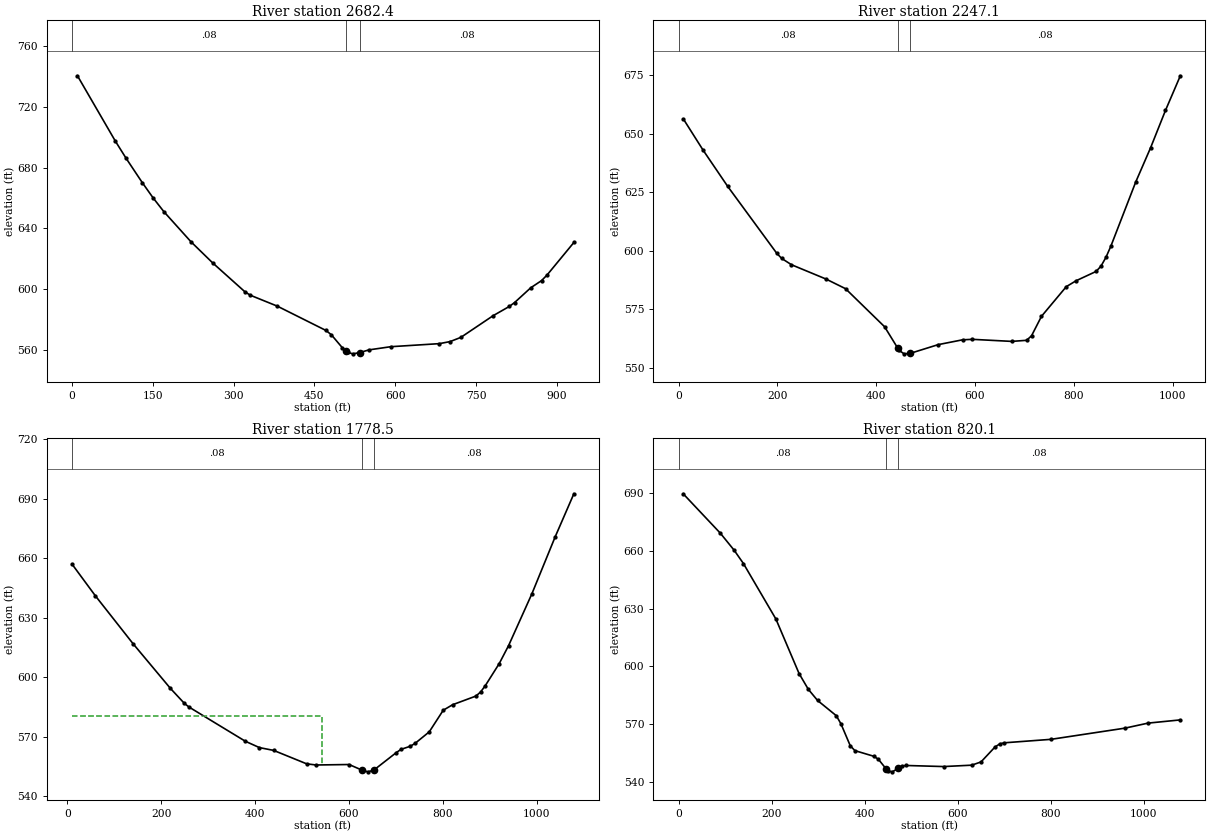
Type RM Length L Ch R = 1 ,2682.4  ,426,435.3,444.6
XS GIS Cut Line= 3
     1554240.739      488985.917     1554231.468      489597.776
     1554226.833      489917.612
#Sta/Elev= 30
      10  740.47    80.3  697.48   100.3  686.14   130.4   670.1   150.5  660.04
   170.5  650.97   220.7  631.19   260.8  617.33     321   598.2     331  595.94
   381.2  588.74   471.5  572.73   481.5  569.89   501.6  561.47   509.1  559.09
   511.6   558.3   521.6  557.34   534.1  558.18   551.7  559.97   591.9  562.04
   681.9  564.05   701.9   565.4   721.9  568.17   781.9  582.47   811.8  588.52
   821.8  591.14   851.8  600.86   871.8  605.57   881.8  609.16   931.8  630.67
#Mann= 3 , 0 , 0
       0     .08       0   509.1    .045       0   534.1     .08       0
Bank Sta=509.1,534.1
XS Rating Curve= 0 ,0
Exp/Cntr=0.3,0.1

Type RM Length L Ch R = 1 ,2247.1  ,504.4,468.6,432.4
XS GIS Cut Line= 4
     1554115.586      489120.341      1553865.28       489347.47
     1553763.303      489625.588     1553869.915      489991.777
#Sta/Elev= 30
     9.9  656.34    49.7  643.06    99.4   627.6   198.8  598.97   208.8  596.77
   228.6  594.08   298.2  587.99     338  583.84     417  567.58     444  558.31
   446.6  557.47   456.5  555.99     469   556.2   525.6  559.93     575  561.99
   594.7  562.19   674.4  561.31   704.5  561.77   714.5  563.72   734.6  572.03
   784.8  584.71   804.8  587.25     845   591.2     855  593.47   865.1  597.25
   875.1  602.06   925.3  629.43   955.4  644.07   985.5  660.02  1015.6  674.85
#Mann= 3 , 0 , 0
       0     .08       0     444    .045       0     469     .08       0
Bank Sta=444,469
XS Rating Curve= 0 ,0
Exp/Cntr=0.3,0.1

Type RM Length L Ch R = 1 ,1778.5  ,937.9,958.3,979
XS GIS Cut Line= 4
      1553332.22      489134.246     1553443.467      489528.247
     1553737.898      489738.844     1553842.103      490028.859
#Sta/Elev= 30
      10  657.01    59.9     641   139.8     617   219.7  594.41   249.6  586.82
   259.6  584.98   379.4  567.78   409.4  564.59   439.6  563.19     510  556.42
   530.1  555.83   600.5  556.07   628.2  553.22   640.7  552.38   653.2  553.25
     701  562.06   711.1  563.69   731.2   565.3   741.2  566.73   771.4  572.54
   801.2  583.43   821.1  586.19   870.8  590.56   880.8  592.62   890.7  595.76
   920.5  606.92   940.4  615.96   990.1  642.07  1039.8  670.82  1079.6  692.49
#Mann= 3 , 0 , 0
      10     .08       0   628.2    .045       0   653.2     .08       0
#XS Ineff= 2 , 0
          543.69  580.69
Permanent Ineff=
       F       F
Bank Sta=628.2,653.2
XS Rating Curve= 0 ,0
Exp/Cntr=0.3,0.1

Type RM Length L Ch R = 1 ,820.1   ,840,820.1,800.2
XS GIS Cut Line= 4
     1552993.843      489203.776     1552952.125      489509.706
     1553021.655      489996.412     1553142.173      490246.719
#Sta/Elev= 30
      10  689.65    89.6  669.24   119.5  660.34   139.4  653.44   209.2  624.62
     259  596.31   278.9   588.1   298.8  582.31   338.9  574.43   348.9  570.24
     369  558.81     379  556.27   419.1  553.38   429.2  551.85   446.8  546.57
   449.2  545.86   459.3  545.26   471.8  547.07   479.3  548.24   489.4  548.56
   569.6     548   629.8  548.72   649.9   550.4     680  558.16     690  559.74
   700.1  560.34   800.4  562.14   959.2  567.95  1008.8  570.56  1078.2  572.23
#Mann= 3 , 0 , 0
       0     .08       0   446.8    .045       0   471.8     .08       0
Bank Sta=446.8,471.8
XS Rating Curve= 0 ,0
Exp/Cntr=0.3,0.1

Chan Stop Cuts=-1
Use User Specified Reach Order=0